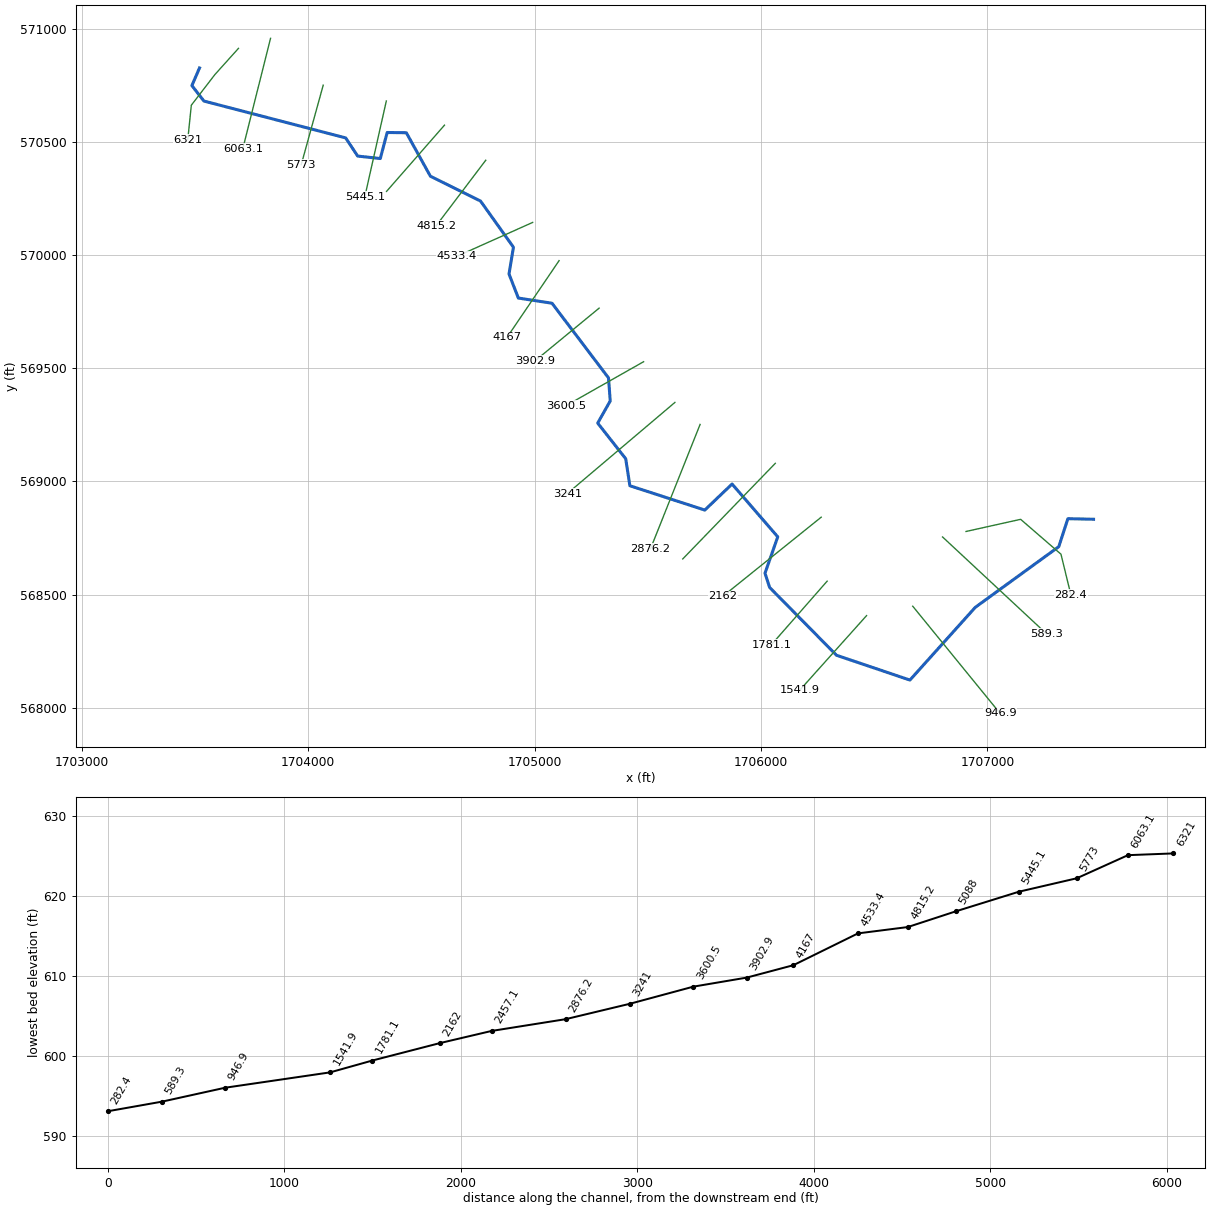
--- LimekilnBr.prj (project) ---

Proj Title=LimekilnBr
Current Plan=p01
Default Exp/Contr=0,0
English Units
Geom File=g01
Flow File=f01
Plan File=p01
BEGIN DESCRIPTION:
AMEC Environment & Infrastructure, 2013
Projection: NAD 1983 State Plane West Virginia South FIPS 4702 (US Feet)
Vertical Datum: NAVD 1988
END DESCRIPTION:
DSS Export Rating Curves= 0
DSS Export Rating Curve Sorted= 0
DSS Export Volume Flow Curves= 0
DXF OffsetX= 0
DXF OffsetY= 0
DXF ScaleX= 0
DXF ScaleY= 0

--- LimekilnBr.p01 (plan) ---

Plan Title=Floodplain
Program Version=4.00
Geom File=g01
Flow File=f01
K Sum by GR=0
Std Step Tol=0.01
Critical Tol=0.01
Num of Std Step Trials=20
Max Error Tol=0.3
Flow Tol Ratio=0.001
Split Flow NTrial=30
Split Flow Tol=0.02
Split Flow Ratio=0.02
Log Output Level=0
Friction Slope Method=1
Unsteady Friction Slope Method=2
Unsteady Bridges Friction Slope Method=1
Global Log Level=0
CheckData=False
Run HTab=0
Run UNet=0
Run PostProcess=0
UNET Theta=0
UNET Theta Warmup=0
UNET ZTol=0
UNET ZSATol=0
UNET MxIter=0
UNET MaxInSteps=0
UNET DtIC=0
UNET DtMin=0
UNET MaxCRTS=0
UNET WFStab=0
UNET SFStab=0
UNET WFX=0
UNET SFX=0
UNET DSS MLevel=0
UNET DZMax Abort=0
UNET Convert EG Bridges=0
UNET Use Existing IB Tables=0
UNET Froude Limit=0
UNET Froude Power=0
Write IC File=0
Echo Input=False
Echo Output=False
Write Detailed=0

--- LimekilnBr.f01 (steady flow) ---

Flow Title=USGS Regress. Eqn. (2010) - Western-Plateaus
Program Version=4.00
Number of Profiles=1
Profile Names=P100yr
River Rch & RM=LimekilnBr,Main      ,6321
     942
River Rch & RM=LimekilnBr,Main      ,5088
     962
River Rch & RM=LimekilnBr,Main      ,1781.1
    1026
River Rch & RM=LimekilnBr,Main      ,282.4
    1041
Boundary for River Rch & Prof#=LimekilnBr,Main      ,1
Up Type=0
Dn Type=3
Dn Slope=0.003457

--- LimekilnBr.g01 (geometry) ---

Geom Title=USGS 3m DEM
Program Version=4.10

River Reach=LimekilnBr      ,Main
Reach XY= 30
     1703520.125      570826.116      1703486.33      570748.275
     1703539.498      570679.915     1704165.583      570517.155
     1704218.752       570436.86     1704318.578      570426.009
      1704348.96      570541.026     1704433.596      570539.941
     1704539.932      570347.884     1704761.286      570238.292
     1704906.686      570034.299     1704887.155      569916.026
     1704928.387       569809.69     1705077.042      569786.903
     1705326.608      569457.042     1705334.203      569355.045
     1705278.865      569257.389     1705402.563      569100.054
     1705421.009      568980.697     1705751.955      568873.275
     1705872.398      568988.292     1706074.221      568755.002
     1706017.797      568594.412     1706038.413      568531.478
     1706333.552      568231.999     1706657.988      568122.407
     1706946.616      568443.587      1707315.54      568711.599
     1707355.688      568835.297     1707469.096      568832.659

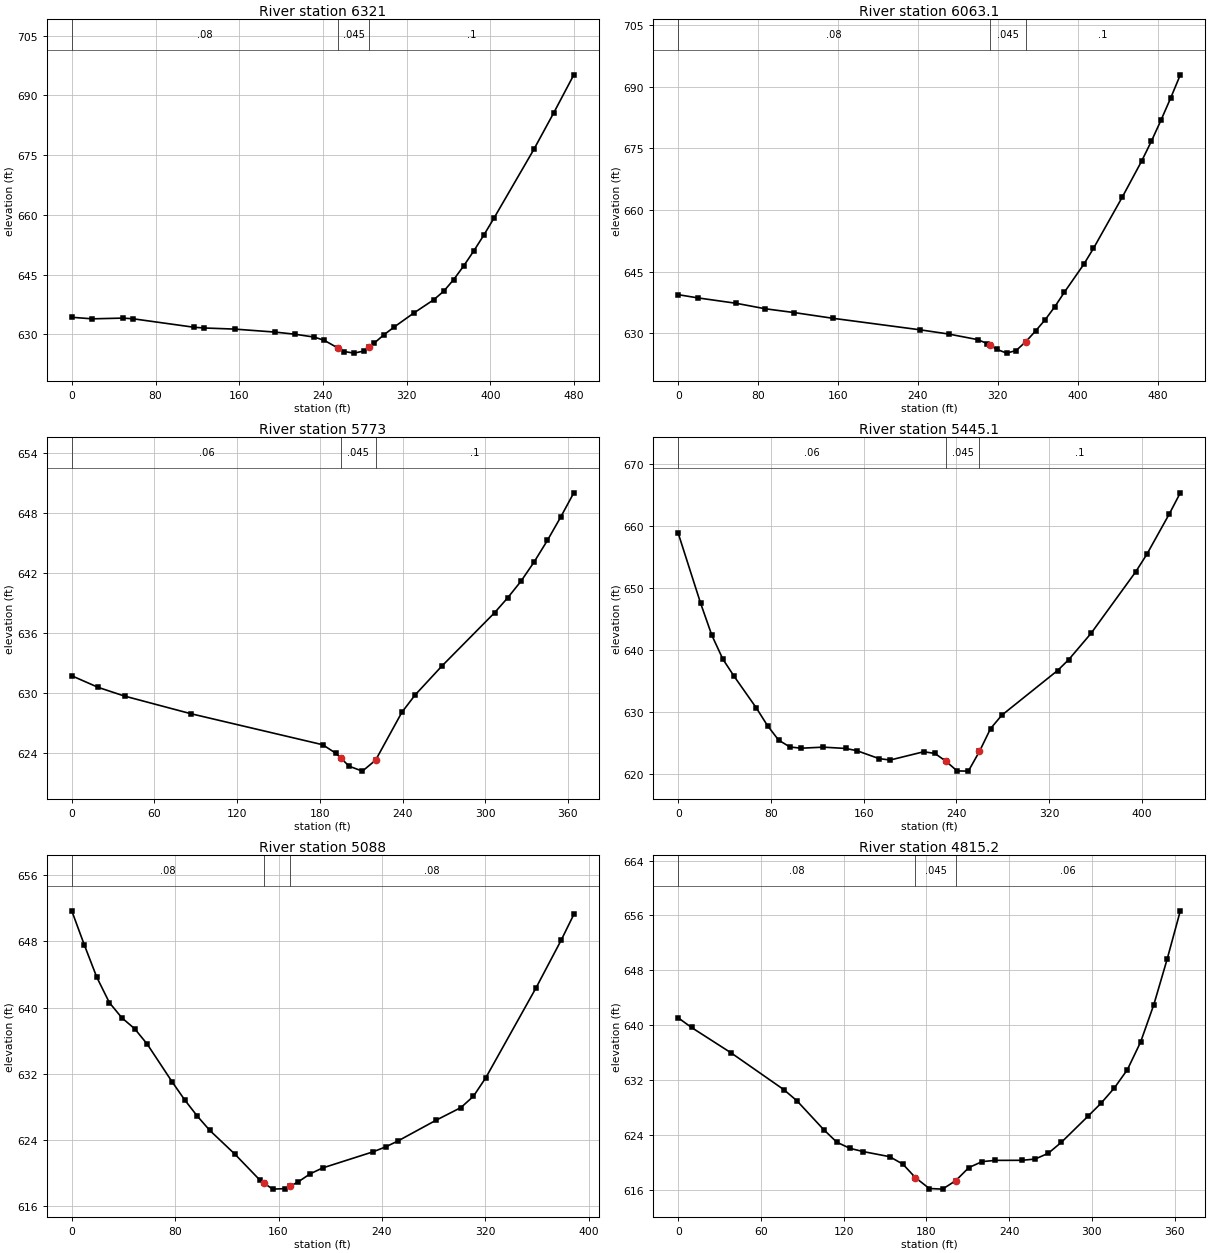
Type RM Length L Ch R = 1 ,6321    ,246.9,257.9,268.9
XS GIS Cut Line= 4
     1703692.201       570912.78     1703588.039      570796.906
     1703483.856      570661.444     1703468.232      570509.345
#Sta/Elev= 30
       0  634.32    19.5  633.93    48.7  634.11    58.4  633.95   116.9  631.81
   126.6  631.63   155.8  631.35   193.8  630.61   212.8  630.08   231.8  629.34
   241.3  628.52   254.7  626.54   260.2  625.72   269.7  625.32   279.2  625.86
   283.9 626.815   288.7  627.79   298.2  629.92   307.7  631.82   326.7  635.38
   345.8  638.72   355.4  640.88   364.9   643.8   374.5  647.25     384  650.96
   393.6  654.93   403.2  659.15   441.4  676.45   460.5  685.68   479.6  695.19
#Mann= 3 , 0 , 0
       0     .08       0   254.7    .045       0   283.9      .1       0
Bank Sta=254.7,283.9
XS Rating Curve= 0 ,0
Exp/Cntr=0.3,0.1

Type RM Length L Ch R = 1 ,6063.1  ,290.4,290.1,289.5
XS GIS Cut Line= 2
     1703833.784      570956.948     1703711.265      570469.314
#Sta/Elev= 27
       0  639.35    19.3  638.58      58  637.25      87  635.92     116  634.99
   154.7   633.6   241.7   630.8   270.7  629.76   299.7   628.4   309.4  627.44
   311.7   627.1   319.1  626.02   328.8   625.1   338.4  625.74   348.1   627.9
   357.8   630.5   367.4  633.23   377.1  636.41   386.8  639.99   406.1  646.75
   415.8  650.63   444.8   663.2   464.1  671.94   473.8  676.76   483.4  681.88
   493.1  687.28   502.8  692.96
#Mann= 3 , 0 , 0
       0     .08       0   311.7    .045       0   348.1      .1       0
Bank Sta=311.7,348.1
XS Rating Curve= 0 ,0
Exp/Cntr=0.3,0.1

Type RM Length L Ch R = 1 ,5773    ,327.4,327.9,327.4
XS GIS Cut Line= 2
     1704066.517      570750.195     1703969.435      570399.098
#Sta/Elev= 20
       0  631.75    19.2  630.59    38.3  629.72    86.3  627.96   182.1  624.85
   191.7  623.99   195.3  623.51   201.3   622.7   210.9  622.21   220.5  623.31
   239.6  628.11   249.2  629.84   268.4   632.7   306.8  638.06   316.3  639.55
   325.9   641.2   335.5  643.14   345.1  645.29   354.7  647.61   364.3  650.06
#Mann= 3 , 0 , 0
       0     .06       0   195.3    .045       0   220.5      .1       0
Bank Sta=195.3,220.5
XS Rating Curve= 0 ,0
Exp/Cntr=0.3,0.1

Type RM Length L Ch R = 1 ,5445.1  ,368.1,357,345.3
XS GIS Cut Line= 2
     1704345.237      570680.336     1704250.271      570257.702
#Sta/Elev= 30
       0   658.8    19.2   647.6    28.9  642.43    38.5  638.55    48.1  635.82
    67.4  630.69      77  627.85    86.6  625.52    96.3  624.42   105.9  624.22
   125.1  624.39   144.4  624.18     154  623.83   173.3  622.54   182.9  622.32
   211.8  623.65   221.4  623.38     231  622.12   240.6  620.56   250.3  620.53
   259.9  623.71   269.5  627.39   279.2  629.54   327.3  636.73   336.9  638.48
   356.2  642.72   394.7  652.62   404.3  655.44   423.6  661.91   433.2  665.34
#Mann= 3 , 0 , 0
       0     .06       0     231    .045       0   259.9      .1       0
Bank Sta=231,259.9
XS Rating Curve= 0 ,0
Exp/Cntr=0.3,0.1

Type RM Length L Ch R = 1 ,5088    ,271.7,272.8,273.8
XS GIS Cut Line= 2
     1704601.994       570573.34     1704346.269      570280.894
#Sta/Elev= 30
       0  651.67     9.7  647.56    19.4  643.64    29.1  640.59    38.8  638.75
    48.6  637.45    58.3   635.6    77.7  631.02    87.4  628.85    97.1   626.9
   106.8  625.17   126.3  622.29   145.7  619.15   148.6  618.83   155.4  618.08
   165.1  618.14   168.6  618.42   174.8  618.91   184.5  619.93   194.2  620.64
   233.1  622.58   242.8  623.17   252.5   623.9   281.6  626.37   301.1  627.92
   310.8  629.28   320.5  631.55   359.4  642.41   378.8  648.15   388.5  651.23
#Mann= 3 , 0 , 0
       0     .08       0   148.6    .045       0   168.6     .08       0
Bank Sta=148.6,168.6
XS Rating Curve= 0 ,0
Exp/Cntr=0.3,0.1

Type RM Length L Ch R = 1 ,4815.2  ,294.6,281.9,268.5
XS GIS Cut Line= 2
     1704784.333      570418.427     1704564.481        570128.1
#Sta/Elev= 30
       0  641.07     9.6  639.67    38.3  635.97    76.7  630.59    86.2  628.96
   105.4   624.8     115  622.95   124.6  622.05   134.2  621.58   153.3  620.84
   162.9  619.76     172  617.79   182.1   616.2   191.7  616.11   201.3  617.35
   210.8  619.25   220.4  620.12     230   620.3   249.2  620.31   258.8  620.49
   268.3  621.32   277.9  622.93   297.1  626.71   306.7  628.63   316.3  630.84
   325.8  633.52   335.4  637.55     345  643.01   354.6  649.59   364.2  656.67
#Mann= 3 , 0 , 0
       0     .08       0     172    .045       0   201.3     .06       0
Bank Sta=172,201.3
XS Rating Curve= 0 ,0
Exp/Cntr=0.3,0.1

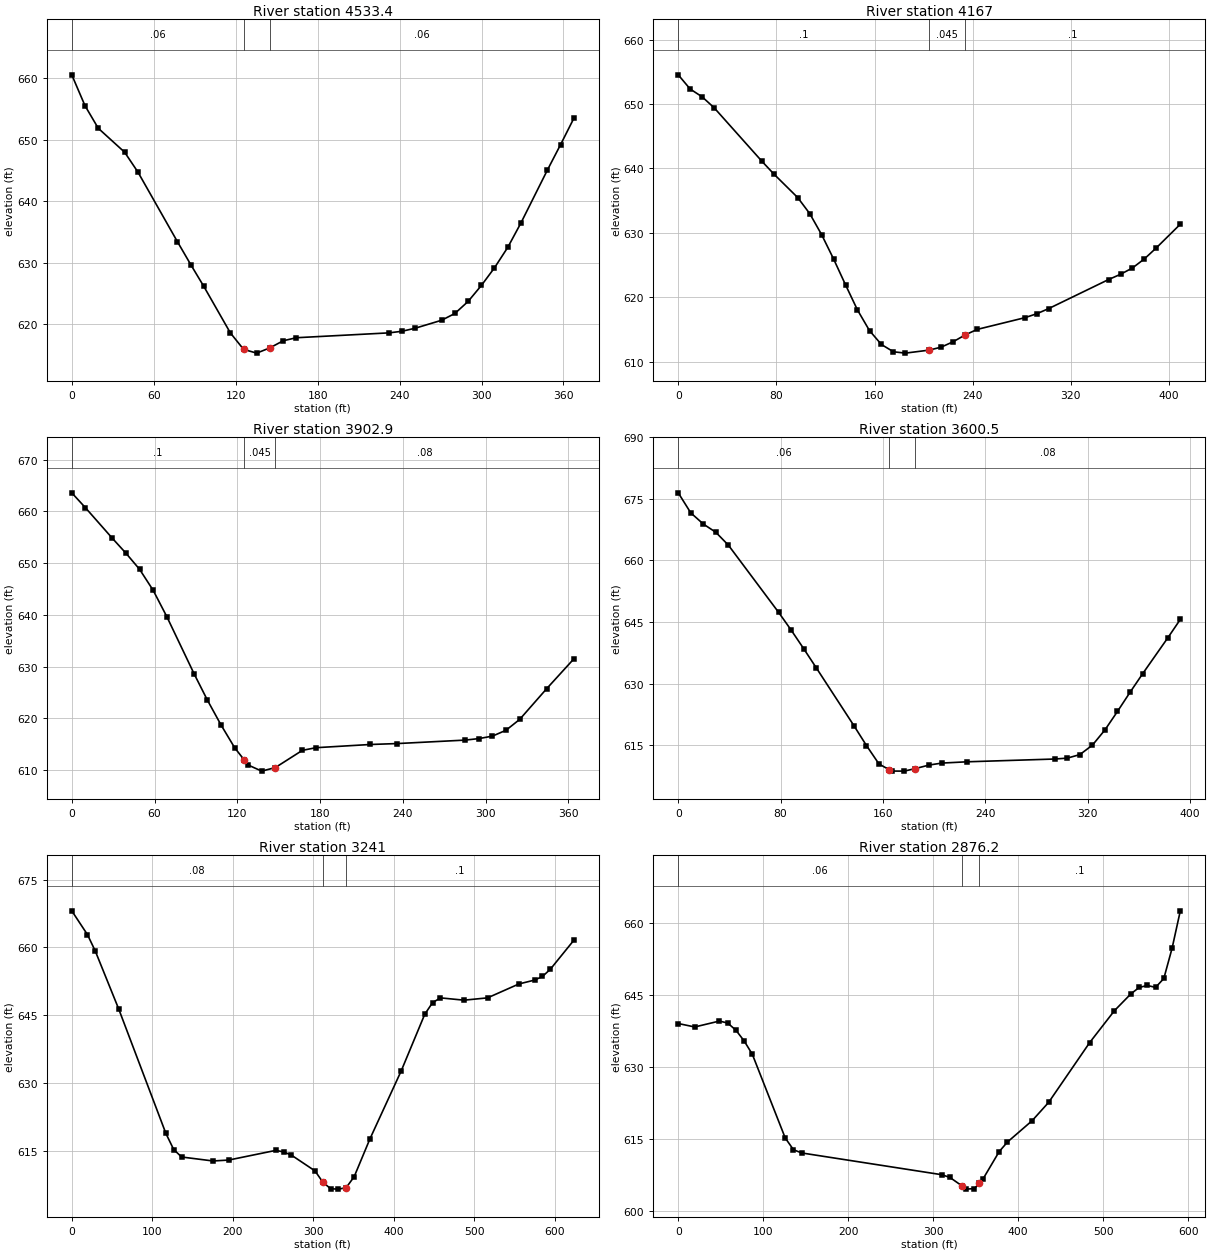
Type RM Length L Ch R = 1 ,4533.4  ,382.7,366.4,373.4
XS GIS Cut Line= 2
     1704991.658      570143.816     1704656.133      569993.703
#Sta/Elev= 27
       0  660.52     9.7   655.5    19.4  651.84    38.7  647.95    48.4  644.74
    77.4   633.4    87.1   629.7    96.7  626.15   116.1  618.61   125.8  615.93
   135.4  615.32   145.1  616.18   154.8  617.33   164.4  617.82   232.2  618.61
   241.8  618.87   251.5  619.37   270.8  620.66   280.5  621.76   290.2  623.72
   299.9  626.31   309.5  629.18   319.2  632.49   328.9  636.48   348.2  645.04
   357.9  649.19   367.6  653.46
#Mann= 3 , 0 , 0
       0     .06       0   125.8    .045       0   145.1     .06       0
Bank Sta=125.8,145.1
XS Rating Curve= 0 ,0
Exp/Cntr=0.3,0.1

Type RM Length L Ch R = 1 ,4167    ,241.6,264.1,263.3
XS GIS Cut Line= 2
     1705108.324      569975.005     1704878.589      569636.406
#Sta/Elev= 30
       0  654.54     9.7  652.34    19.5  651.12    29.2  649.44    68.2  641.12
    77.9  639.15    97.4  635.48   107.2  632.99   116.9  629.72   126.6  625.96
   136.4  621.92   146.1  618.03   155.9  614.83   165.6  612.68   175.4  611.55
   185.1  611.34   204.6  611.81   214.3  612.27   224.1  613.11   233.8  614.16
   243.6  615.02   282.5  616.84   292.3  617.46     302  618.26   350.7  622.76
   360.5  623.58   370.2  624.56     380  625.98   389.7  627.69   409.2  631.35
#Mann= 3 , 0 , 0
       0      .1       0   204.6    .045       0   233.8      .1       0
Bank Sta=204.6,233.8
XS Rating Curve= 0 ,0
Exp/Cntr=0.3,0.1

Type RM Length L Ch R = 1 ,3902.9  ,307.7,302.4,296.5
XS GIS Cut Line= 2
     1705285.112      569765.108     1705003.962       569533.88
#Sta/Elev= 26
       0  663.59     9.8  660.74    29.5  654.78    39.4  651.88    49.2  648.79
      59  644.75    68.9  639.66    88.6  628.65    98.4  623.48   108.2  618.72
   118.1  614.31   124.8  612.03   127.9  610.97   137.7  609.79   147.6  610.48
   167.2  613.81   177.1  614.32   216.4  614.94   236.1  615.12   285.3  615.79
   295.2  616.08     305  616.56   314.8  617.69   324.7  619.78   344.3  625.73
     364  631.49
#Mann= 3 , 0 , 0
       0      .1       0   124.8    .045       0   147.6     .08       0
Bank Sta=124.8,147.6
XS Rating Curve= 0 ,0
Exp/Cntr=0.3,0.1

Type RM Length L Ch R = 1 ,3600.5  ,354.4,359.5,364.5
XS GIS Cut Line= 2
     1705481.566      569528.525      1705140.18      569335.133
#Sta/Elev= 29
       0  676.46     9.8  671.58    19.6  668.86    29.4  666.84    39.2  663.71
    78.5  647.32    88.3     643    98.1  638.47   107.9  633.82   137.3  619.74
   147.1   614.9   156.9   610.4     165  608.99   166.8  608.68   176.6  608.66
     185  609.26   196.2  610.15     206  610.62   225.6  610.93   294.3  611.61
   304.1  611.83   313.9  612.69   323.7  614.99   333.5   618.7   343.3  623.21
   353.1  627.86   362.9  632.36   382.6  641.12   392.4  645.62
#Mann= 3 , 0 , 0
       0     .06       0     165    .045       0     185     .08       0
Bank Sta=165,185
XS Rating Curve= 0 ,0
Exp/Cntr=0.3,0.1

Type RM Length L Ch R = 1 ,3241    ,353.3,364.8,376.9
XS GIS Cut Line= 2
     1705619.954      569348.772     1705144.165      568945.847
#Sta/Elev= 30
       0   668.1    19.5  662.83    29.2   659.2    58.4  646.33   116.9  618.83
   126.6  615.28   136.4  613.63   175.4  612.75   194.8  612.95   253.3  615.09
     263  614.76   272.8  614.04     302  610.56   311.7  608.09   321.5   606.6
   331.2  606.52   340.7  606.83   350.7  609.27   370.2  617.61   409.2  632.72
   438.4  645.23   448.1  647.79   457.9  648.84   487.1  648.33   516.3  648.84
   555.3  651.92   574.8  652.78   584.5  653.58   594.2  655.15   623.5  661.59
#Mann= 3 , 0 , 0
       0     .08       0   311.7    .045       0   340.7      .1       0
Bank Sta=311.7,340.7
XS Rating Curve= 0 ,0
Exp/Cntr=0.3,0.1

Type RM Length L Ch R = 1 ,2876.2  ,428.3,419.1,407.9
XS GIS Cut Line= 2
     1705731.103      569251.533      1705512.34      568702.756
#Sta/Elev= 30
       0  639.11    19.4  638.39    48.4  639.62    58.1  639.22    67.8  637.73
    77.5   635.5    87.2  632.69   125.9  615.25   135.6   612.8   145.3  612.13
   309.9   607.6   319.6  607.04   334.1  605.24     339  604.59   348.6  604.71
   354.1  605.79   358.3  606.61   377.7  612.42   387.4  614.41   416.4  618.85
   435.8  622.66   484.2  635.15   513.3  641.79   532.7   645.3   542.4  646.63
     552  647.04   561.7  646.64   571.4   648.5   581.1  654.79   590.8   662.6
#Mann= 3 , 0 , 0
       0     .06       0   334.1    .045       0   354.1      .1       0
Bank Sta=334.1,354.1
XS Rating Curve= 0 ,0
Exp/Cntr=0.3,0.1

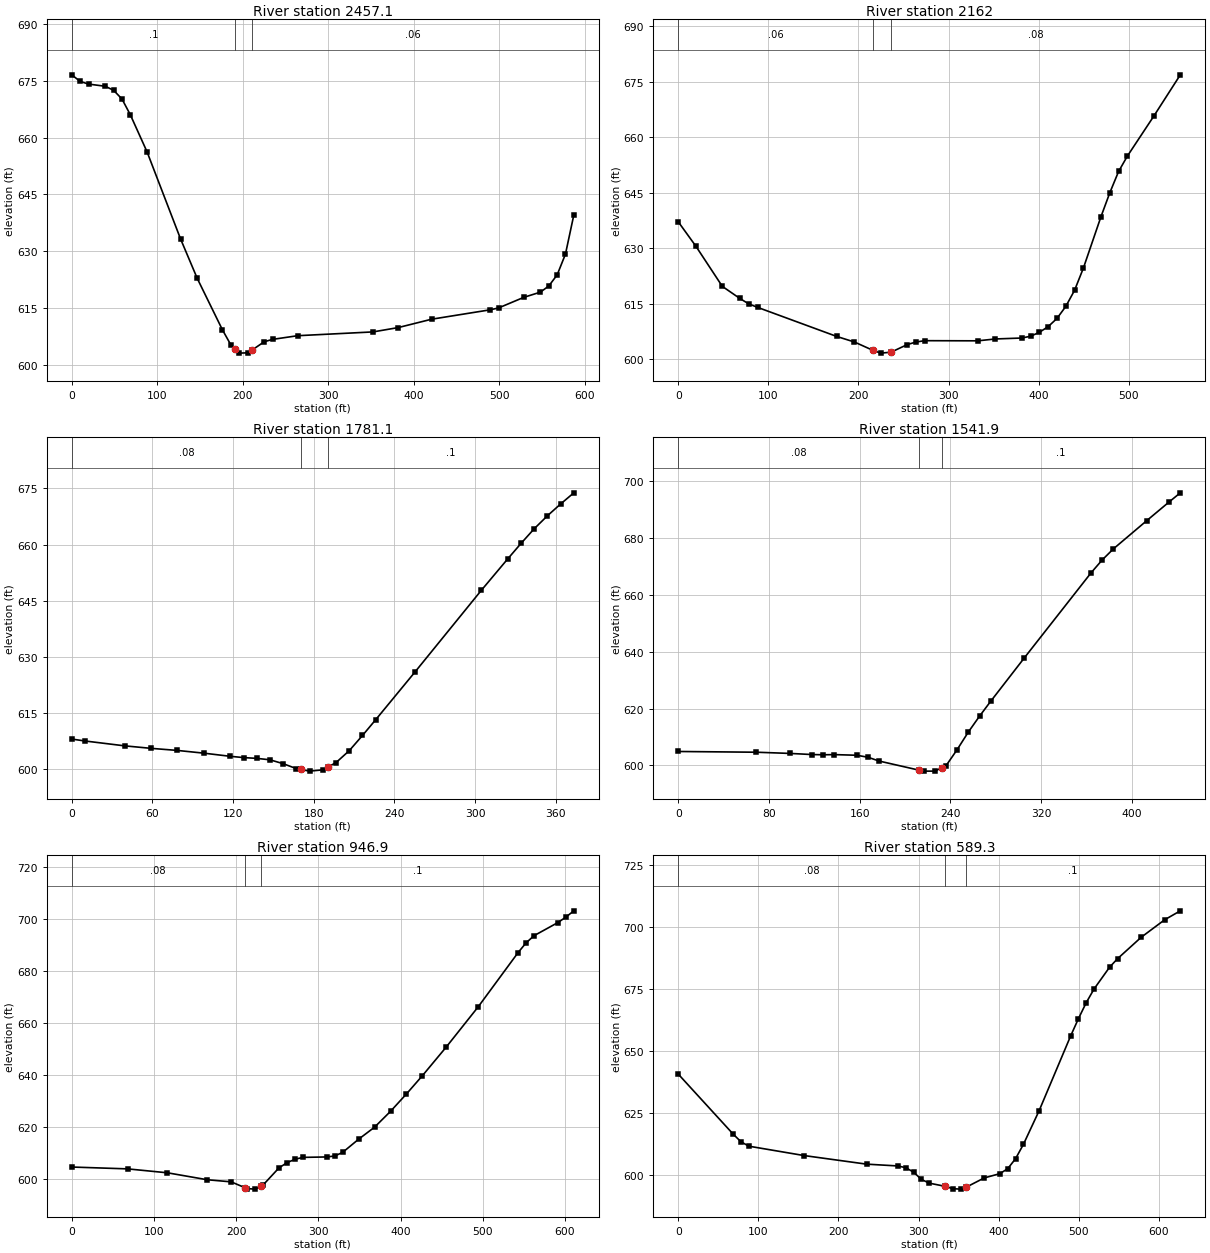
Type RM Length L Ch R = 1 ,2457.1  ,295.9,295,298.4
XS GIS Cut Line= 2
     1706063.263      569079.589     1705654.743      568657.617
#Sta/Elev= 30
       0  676.57     9.8  674.83    19.6  674.13    39.2  673.55    48.9  672.49
    58.7   670.2    68.5  666.03    88.1  656.22   127.2  633.29   146.8  622.83
   176.2  609.28     186  605.33   191.1  604.18   195.8  603.12   205.6   603.2
   211.1  603.96   225.1  606.12   234.9  606.75   264.3  607.72   352.4  608.72
   381.8  609.86   420.9  612.07   489.4  614.55   499.2  615.04   528.6  617.83
   548.2  619.22     558  620.84   567.8  623.78   577.5  629.26   587.3  639.62
#Mann= 3 , 0 , 0
       0      .1       0   191.1    .045       0   211.1     .06       0
Bank Sta=191.1,211.1
XS Rating Curve= 0 ,0
Exp/Cntr=0.3,0.1

Type RM Length L Ch R = 1 ,2162    ,378.7,380.9,378.6
XS GIS Cut Line= 2
     1706266.002      568841.745     1705831.887      568492.657
#Sta/Elev= 30
       0  637.14    19.6  630.52    48.9  619.66    68.4  616.38    78.2  614.92
      88  613.98   175.9   606.1   195.5   604.6   216.1  602.34   224.8  601.59
   236.1  601.84   254.1   603.9   263.9   604.6   273.6  604.96   332.3  604.92
   351.8  605.42   381.2  605.68   390.9  606.16   400.7  607.22   410.5  608.77
   420.2  610.97     430  614.22   439.8  618.61   449.6  624.64   469.1  638.54
   478.9  645.01   488.6  650.75   498.4  654.93   527.7  665.74   557.1  676.91
#Mann= 3 , 0 , 0
       0     .06       0   216.1    .045       0   236.1     .08       0
Bank Sta=216.1,236.1
XS Rating Curve= 0 ,0
Exp/Cntr=0.3,0.1

Type RM Length L Ch R = 1 ,1781.1  ,239.8,239.2,238.7
XS GIS Cut Line= 2
     1706292.471      568559.368     1706046.243      568278.625
#Sta/Elev= 28
       0  607.99     9.8  607.48    39.3  606.18      59  605.51    78.6  604.95
    98.3  604.22   117.9  603.38   127.8  603.04   137.6  602.83   147.4  602.45
   157.2  601.41   167.1  600.08   170.4  599.86   176.9  599.42   186.7  599.76
   190.4  600.49   196.5  601.69   206.4   604.9   216.2  608.95     226  613.15
   255.5  626.03   304.6  647.76   324.3  656.19   334.1  660.29   343.9  664.21
   353.8   667.7   363.6  670.85   373.4  673.82
#Mann= 3 , 0 , 0
       0     .08       0   170.4    .045       0   190.4      .1       0
Bank Sta=170.4,190.4
XS Rating Curve= 0 ,0
Exp/Cntr=0.3,0.1

Type RM Length L Ch R = 1 ,1541.9  ,559.6,595,629.7
XS GIS Cut Line= 2
     1706466.521      568407.114     1706171.116      568077.451
#Sta/Elev= 25
       0  604.86    68.9   604.6    98.4  604.18     118  603.78   127.9   603.7
   137.7  603.76   157.4  603.53   167.2  602.84   177.1  601.49   212.5  598.26
   216.4  597.94   226.2  597.94   232.5  599.16   236.1  599.86   245.9  605.54
   255.8  611.75   265.6   617.3   275.4  622.52   304.9  637.74     364  667.84
   373.8  672.37   383.6  676.24   413.1  686.22   432.8   692.8   442.6  695.99
#Mann= 3 , 0 , 0
       0     .08       0   212.5    .045       0   232.5      .1       0
Bank Sta=212.5,232.5
XS Rating Curve= 0 ,0
Exp/Cntr=0.3,0.1

Type RM Length L Ch R = 1 ,946.9   ,353.2,357.6,361.2
XS GIS Cut Line= 2
     1706670.302      568448.719     1707056.216      567975.258
#Sta/Elev= 30
       0  604.52    67.9  603.81   116.4   602.3   164.8  599.63   193.9  598.82
   210.5   596.6   213.3  596.23     223  596.02   230.5  597.23   232.7  597.59
   252.1   604.2   261.8  606.18   271.5   607.5   281.2  608.23   310.3   608.4
     320  608.77   329.6  610.17     349  615.23   368.4  619.86   387.8  625.95
   407.2  632.65   426.6  639.67   455.7  650.73   494.5  666.17     543  687.02
   552.6  690.72   562.3  693.49   591.4  698.56   601.1  700.65   610.8  703.07
#Mann= 3 , 0 , 0
       0     .08       0   210.5    .045       0   230.5      .1       0
Bank Sta=210.5,230.5
XS Rating Curve= 0 ,0
Exp/Cntr=0.3,0.1

Type RM Length L Ch R = 1 ,589.3   ,305.9,306.9,309.3
XS GIS Cut Line= 2
     1706802.098      568754.546      1707260.59      568327.385
#Sta/Elev= 30
       0  640.65    68.5  616.47    78.3  613.37    88.1  611.59   156.7  607.83
     235  604.35   274.2  603.62     284  602.91   293.7  601.13   303.5  598.19
   313.3  596.69   332.9  595.42   342.7  594.46   352.5  594.28   358.9  594.98
   381.9   598.8   401.4  600.52   411.2  602.52     421  606.56   430.8  612.33
   450.4   625.9   489.6  655.93   499.4  662.96   509.2  669.45   518.9  674.93
   538.5  683.81   548.3  687.17   577.7  695.78   607.1  702.86   626.6  706.46
#Mann= 3 , 0 , 0
       0     .08       0   332.9    .045       0   358.9      .1       0
Bank Sta=332.9,358.9
XS Rating Curve= 0 ,0
Exp/Cntr=0.3,0.1

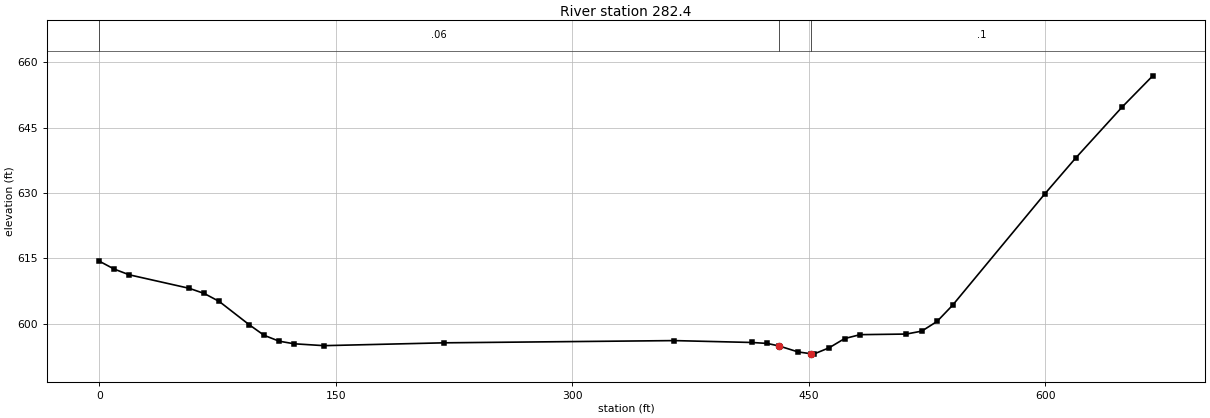
Type RM Length L Ch R = 1 ,282.4   ,294.4,282.4,268.6
XS GIS Cut Line= 4
     1706905.941       568778.72     1707147.055      568832.385
     1707325.169      568678.382     1707369.127      568498.053
#Sta/Elev= 30
       0  614.37     9.5  612.55      19  611.25      57  608.16    66.5  606.98
      76  605.16      95  599.83   104.5  597.39     114  596.05   123.5  595.45
   142.5  595.02   218.5  595.67   364.7  596.18   413.8  595.75   423.6  595.53
   431.1  594.95   443.2  593.58   451.1  593.18     453  593.08   462.8  594.52
   472.7  596.65   482.5  597.54   511.8  597.68   521.6  598.35   531.3  600.57
   541.1  604.26   599.7  629.82   619.2     638   648.6  649.66   668.1  656.84
#Mann= 3 , 0 , 0
       0     .06       0   431.1    .045       0   451.1      .1       0
Bank Sta=431.1,451.1
XS Rating Curve= 0 ,0
Exp/Cntr=0.3,0.1

Chan Stop Cuts=-1
Use User Specified Reach Order=0
Composite Channel Slope=5